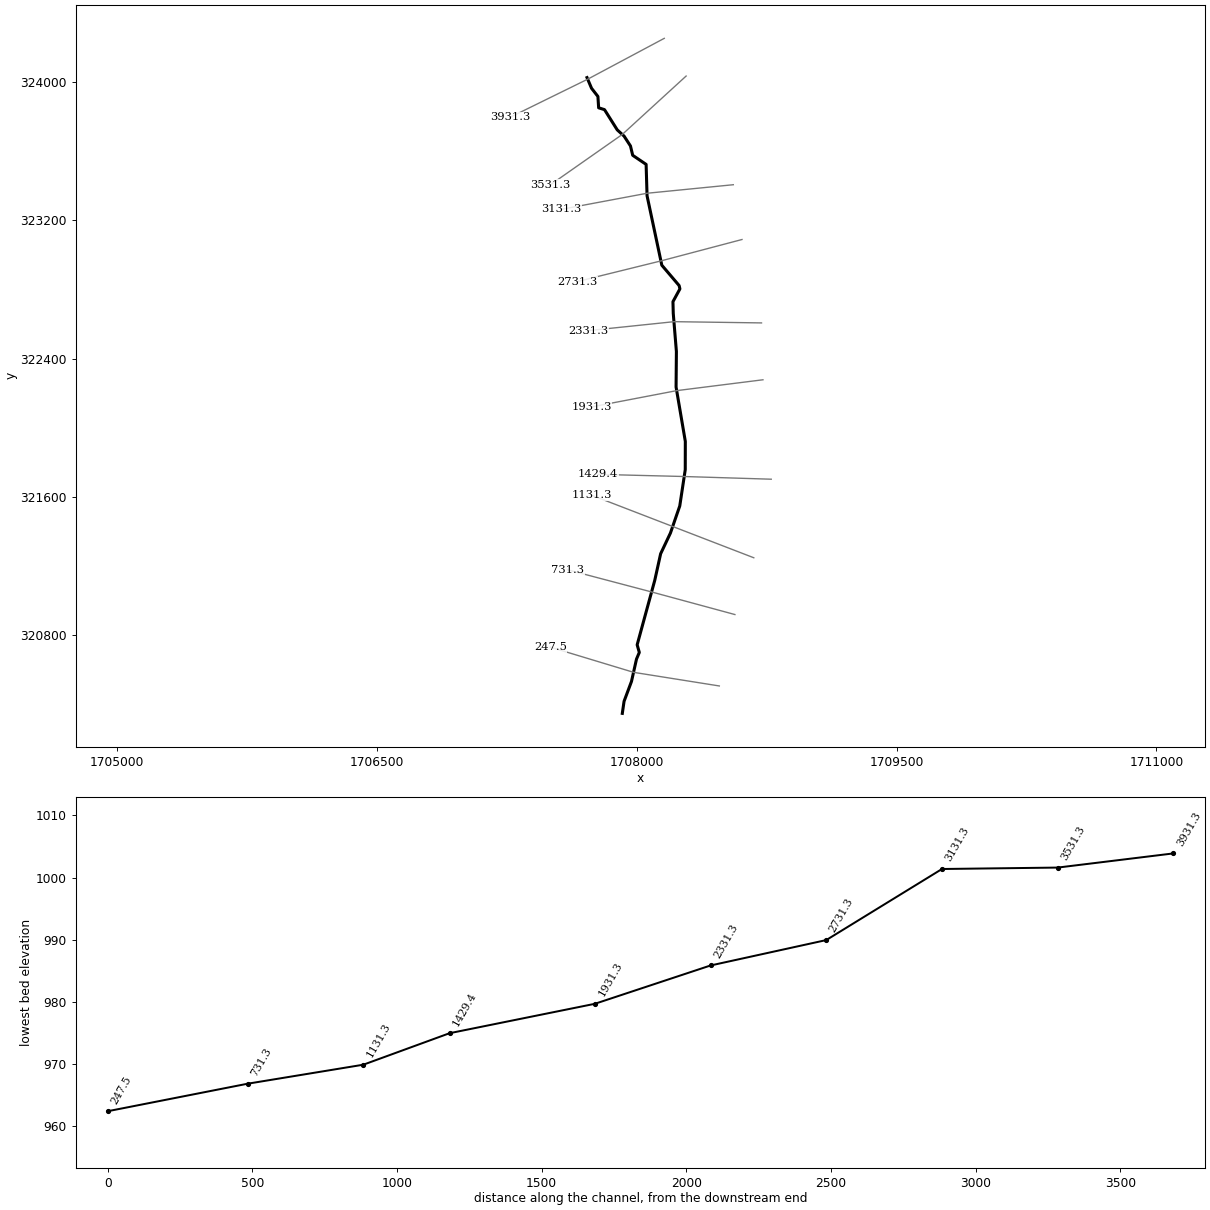
--- BennetRn.prj (project) ---

Proj Title=BennetRn
Current Plan=p01
Geom File=g01
Flow File=f01
Plan File=p01
DSS Export Rating Curves=0
DSS Export Rating Curve Sorted=0
DSS Export Volume Flow Curves=0
DXF OffsetX=0
DXF OffsetY=0
DXF ScaleX=0
DXF ScaleY=0

--- BennetRn.p01 (plan) ---

Plan Title=Floodplain
Program Version=4.00
Geom File=g01
Flow File=f01
K Sum by GR=0
Std Step Tol=0.01
Critical Tol=0.01
Num of Std Step Trials=20
Max Error Tol=0.3
Flow Tol Ratio=0.001
Split Flow NTrial=30
Split Flow Tol=0.02
Split Flow Ratio=0.02
Log Output Level=0
Friction Slope Method=1
Unsteady Friction Slope Method=2
Unsteady Bridges Friction Slope Method=1
Global Log Level=0
CheckData=False
Run HTab=0
Run UNet=0
Run PostProcess=0
UNET Theta=0
UNET Theta Warmup=0
UNET ZTol=0
UNET ZSATol=0
UNET MxIter=0
UNET MaxInSteps=0
UNET DtIC=0
UNET DtMin=0
UNET MaxCRTS=0
UNET WFStab=0
UNET SFStab=0
UNET WFX=0
UNET SFX=0
UNET DSS MLevel=0
UNET DZMax Abort=0
UNET Convert EG Bridges=0
UNET Use Existing IB Tables=0
UNET Froude Limit=0
UNET Froude Power=0
Write IC File=0
Echo Input=False
Echo Output=False
Write Detailed=0

--- BennetRn.f01 (steady flow) ---

Flow Title=NFF Regression Equation
Program Version=4.00
Number of Profiles=1
Profile Names=P100yr
River Rch & RM=BennetRn,Main      ,3931.3
851.4480
River Rch & RM=BennetRn,Main      ,2731.3
866.6811
River Rch & RM=BennetRn,Main      ,2731.3
972.1262
River Rch & RM=BennetRn,Main      ,247.5
1040.488
Boundary for River Rch & Prof#=BennetRn,Main      ,1
Up Type=0
Dn Type=3
Dn Slope=0.010582

--- BennetRn.g01 (geometry) ---

Geom Title=USGS 3m DEM
Program Version=4.00

River Reach=BennetRn     ,Main
Reach XY= 30
     1707712.495      324026.672     1707738.682      323964.791
     1707775.434      323917.479     1707779.657      323851.797
     1707813.448      323841.238     1707887.157      323724.020
     1707926.442      323688.118     1707963.401      323631.092
     1707976.284      323577.026     1708053.795      323524.437
     1708059.285      323342.593     1708144.399      322941.101
     1708244.298      322823.465     1708248.942      322804.034
     1708208.815      322730.113     1708210.505      322662.530
     1708228.667      322441.614     1708226.766      322236.117
     1708280.199      321921.430     1708279.778      321757.962
     1708248.099      321548.027     1708194.244      321391.319
     1708137.640      321271.356     1708103.638      321117.389
     1708002.051      320744.624     1708014.511      320700.483
     1707998.248      320661.832     1707969.316      320532.578
     1707926.439      320417.472     1707916.304      320347.777

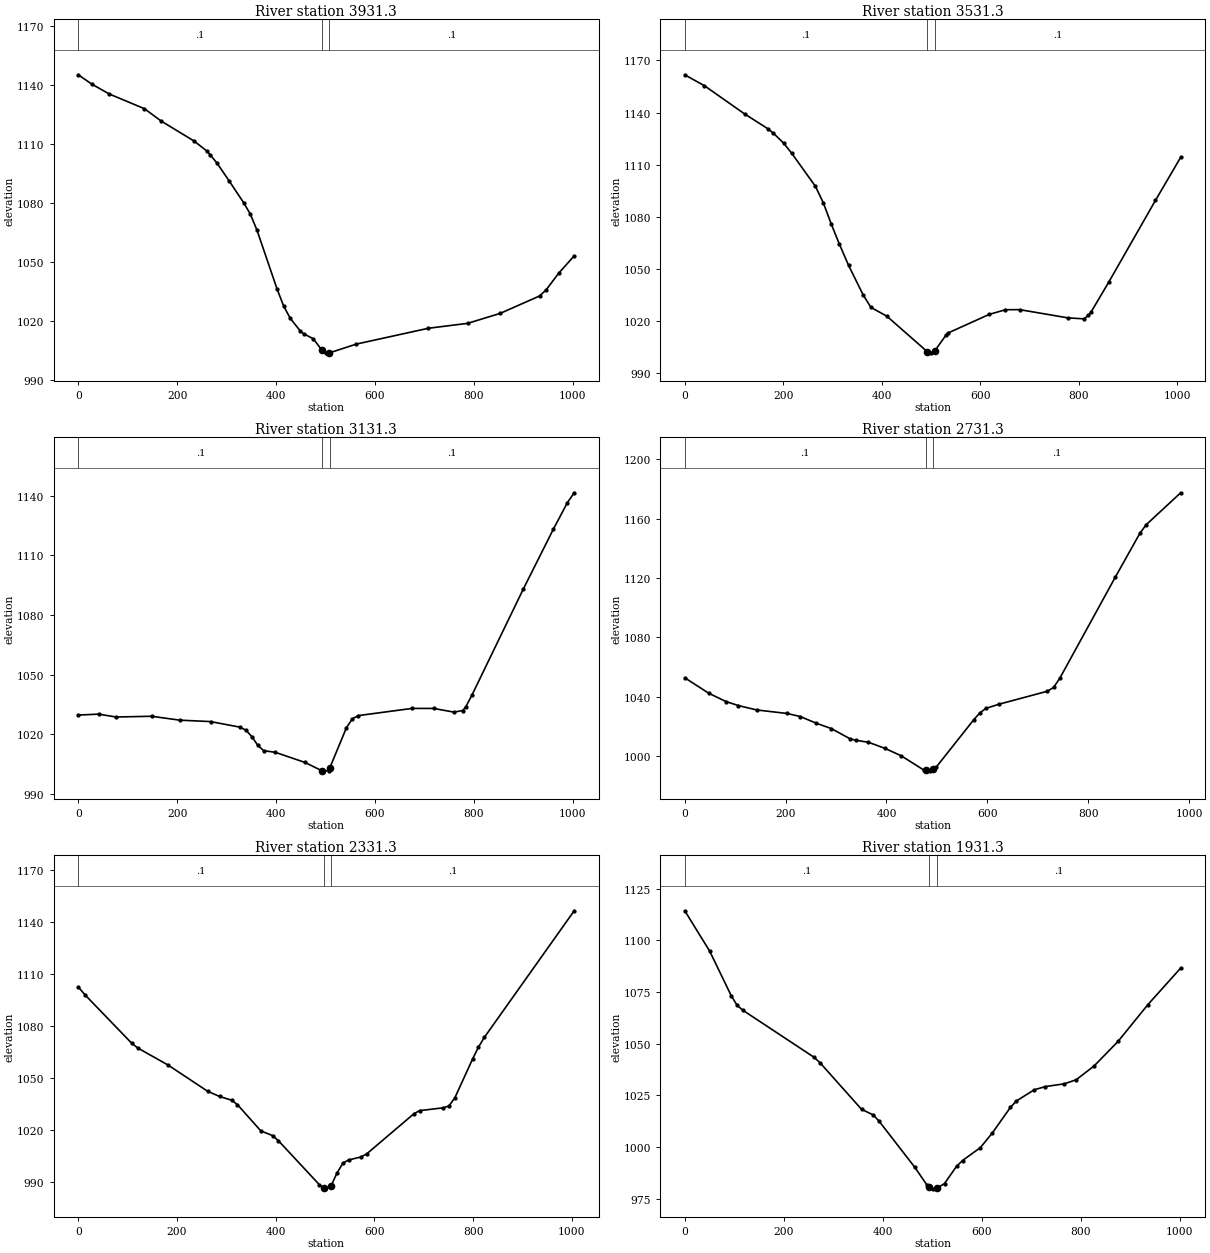
Type RM Length L Ch R = 1 ,3931.3,390.501,400,401.899
XS GIS Cut Line= 3
     1708158.655      324253.823     1707717.621      324018.086
     1707266.738      323796.237
#Sta/Elev= 30
       0 1145.14    27.6 1140.36    62.7 1135.39   133.5 1127.97   167.9 1121.62
   234.2 1111.51   259.4 1106.56   267.1 1104.42   280.6 1100.26   304.9 1091.31
   335.0 1079.97   347.9 1074.39   361.4 1066.20   401.8 1036.45   415.2 1027.78
   428.7 1021.47   448.7 1015.20   455.6 1013.72   475.0 1011.19   492.6 1005.38
   501.3 1003.89   507.6 1004.02   562.2 1008.48   707.8 1016.51   787.2 1019.00
   853.3 1024.09   932.7 1032.90   945.9 1035.98   971.4 1044.47  1002.6 1053.24
#Mann= 3 , 0 , 0
       0     0.1       0   492.6   0.045       0   507.6     0.1       0
Bank Sta=   492.6,   507.6
Exp/Cntr=0.3,0.1

Type RM Length L Ch R = 1 ,3531.3,414.455,400,390.225
XS GIS Cut Line= 3
     1708284.837      324035.678     1707916.056      323697.610
     1707501.365      323406.486
#Sta/Elev= 30
       0 1161.70    39.8 1155.45   121.7 1139.16   168.7 1130.69   179.8 1128.16
   200.9 1122.34   217.0 1116.65   265.3 1097.56   281.4 1088.03   297.4 1075.92
   313.6 1064.54   332.5 1052.16   361.9 1035.27   378.0 1027.92   410.3 1022.87
   492.8 1002.36   499.1 1001.61   507.8 1002.94   530.3 1011.92   535.2 1013.27
   618.4 1023.90   651.3 1026.58   680.3 1026.62   778.2 1021.89   810.9 1021.33
   819.6 1023.34   825.4 1025.38   860.9 1042.38   955.9 1089.48  1007.0 1114.20
#Mann= 3 , 0 , 0
       0     0.1       0   492.8   0.045       0   507.8     0.1       0
Bank Sta=   492.8,   507.8
Exp/Cntr=0.3,0.1

Type RM Length L Ch R = 1 ,3131.3,396.4,400,401.257
XS GIS Cut Line= 3
     1708557.303      323406.794     1708058.633      323357.323
     1707565.299      323264.543
#Sta/Elev= 30
       0 1029.61    40.8 1030.07    76.6 1028.63   148.2 1029.00   204.8 1027.05
   267.5 1026.32   327.1 1023.52   339.1 1021.96   351.0 1018.76   362.9 1014.44
   374.9 1011.69   398.7 1010.83   458.4 1005.77   493.6 1001.46   494.2 1001.38
   506.2 1001.62   508.6 1002.95   542.4 1023.23   554.5 1027.76   566.6 1029.35
   675.3 1032.96   718.8 1032.94   759.9 1031.09   777.8 1031.90   784.0 1033.86
   796.1 1039.54   899.8 1092.85   960.8 1123.09   989.4 1136.56  1003.1 1141.50
#Mann= 3 , 0 , 0
       0     0.1       0   493.6   0.045       0   508.6     0.1       0
Bank Sta=   493.6,   508.6
Exp/Cntr=0.3,0.1

Type RM Length L Ch R = 1 ,2731.3,406.402,400,396.64
XS GIS Cut Line= 3
     1708607.467      323089.738     1708138.338      322965.617
     1707654.749      322846.037
#Sta/Elev= 30
       0 1052.80    47.6 1042.38    81.6 1036.83   106.2 1034.10   143.0 1031.12
   203.0 1028.77   229.0 1026.71   261.2 1022.14   290.4 1018.65   327.2 1011.81
   338.9 1010.72   364.1 1009.40   397.2 1005.24   429.5 1000.22   474.6  990.53
   477.8  990.37   486.9  989.94   492.8  991.15   499.1  992.84   572.8 1024.43
   584.7    1029   597.0 1032.18   623.6 1035.05   719.3 1043.76   731.5 1046.33
   743.7 1052.46   853.8 1120.56   902.7 1150.17   914.9 1155.83   983.4 1177.38
#Mann= 3 , 0 , 0
       0     0.1       0   477.8   0.045       0   492.8     0.1       0
Bank Sta=   477.8,   492.8
Exp/Cntr=0.3,0.1

Type RM Length L Ch R = 1 ,2331.3,396.84,400,401.93
XS GIS Cut Line= 3
     1708720.194      322607.151     1708215.542      322614.343
     1707718.491      322562.389
#Sta/Elev= 30
       0 1102.63    13.5 1098.14   108.5 1070.05   120.4 1067.41   181.9 1057.54
   261.9 1042.41   286.0 1039.41   310.4 1037.26   322.3 1034.69   369.8 1019.49
   393.5 1016.79   405.4 1013.81   488.5  988.35   497.2  986.59   500.4  985.85
   512.2  987.89   524.2  995.23   536.2 1000.96   548.1 1002.74   572.0 1004.40
   583.9 1006.14   679.4 1029.30   691.3 1031.21   739.1 1032.83   751.0 1033.94
   763.0 1038.75   798.8 1061.10   810.7 1067.95   822.7 1073.61  1004.5 1146.68
#Mann= 3 , 0 , 0
       0     0.1       0   497.2   0.045       0   512.2     0.1       0
Bank Sta=   497.2,   512.2
Exp/Cntr=0.3,0.1

Type RM Length L Ch R = 1 ,1931.3,505.419,501.921,497.099
XS GIS Cut Line= 3
     1708728.560      322278.127     1708230.748      322215.363
     1707739.433      322121.085
#Sta/Elev= 30
       0 1114.22    50.3 1094.73    93.9 1073.14   105.8 1068.51   117.8 1066.08
   261.4 1043.39   273.4 1040.75   357.1 1018.28   381.1 1015.52   393.0 1012.41
   464.4  990.36   488.8  981.87   494.3  980.76   500.7  979.68   509.3  980.08
   524.9  982.40   549.1  990.69   561.2  993.49   597.4  999.76   621.6 1006.87
   657.9 1019.15   670.0 1022.29   706.2 1027.70   728.9 1029.27   766.7 1030.57
   790.9 1032.55   827.1 1039.21   875.5 1051.08   935.9 1068.89  1002.0 1086.52
#Mann= 3 , 0 , 0
       0     0.1       0   494.3   0.045       0   509.3     0.1       0
Bank Sta=   494.3,   509.3
Exp/Cntr=0.3,0.1

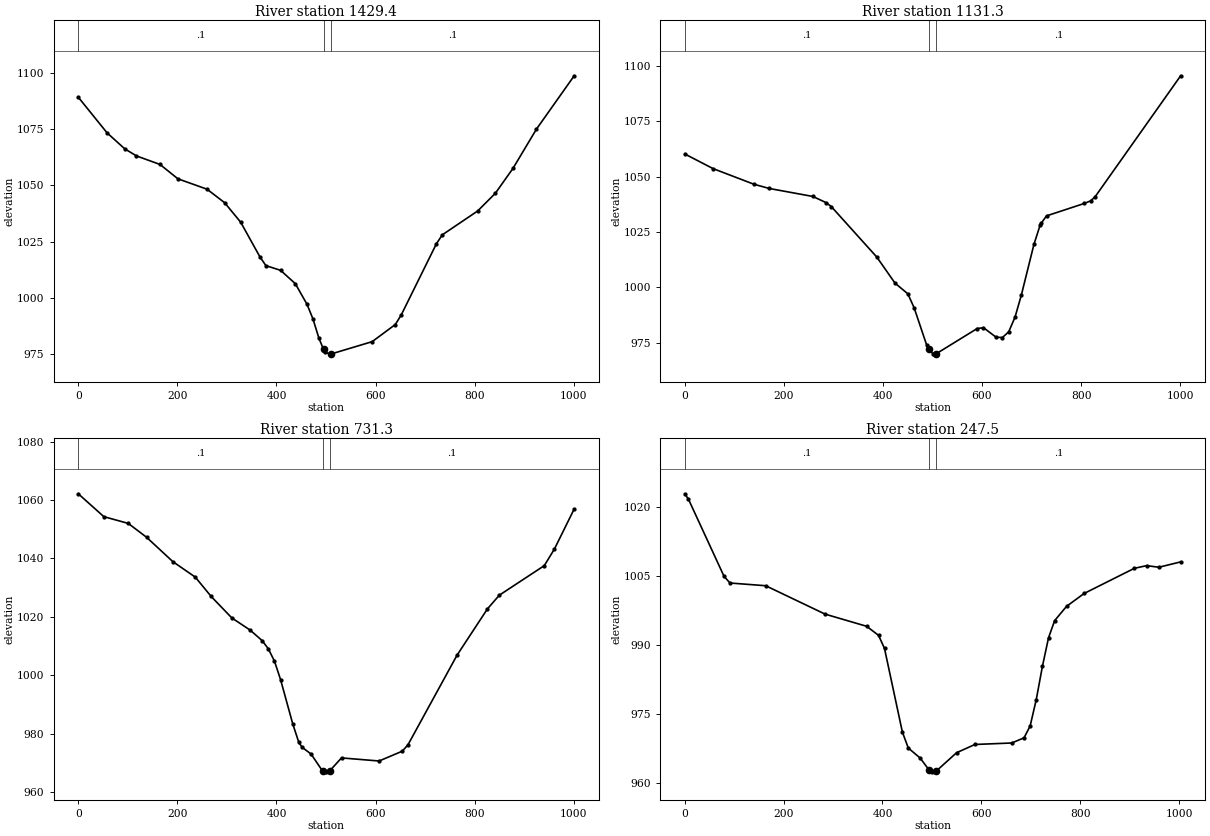
Type RM Length L Ch R = 1 ,1429.4,305.707,298.079,290.33
XS GIS Cut Line= 3
     1708776.464      321702.753     1708276.317      321718.274
     1707775.716      321730.851
#Sta/Elev= 30
       0 1089.20    58.0 1073.38    93.6 1066.29   117.4 1063.11   164.9 1059.32
   201.0 1052.94   259.9 1048.30   295.5 1042.28   327.8 1033.63   366.8 1018.15
   378.7 1014.32   408.4 1012.22   438.1 1006.29   461.8  997.08   473.7  990.62
   485.6  982.14   495.1  977.02   497.5  975.81   509.3  974.95   510.1  975.00
   593.3  980.50   640.0  988.12   651.9  992.35   723.1 1024.10   735.0 1028.03
   806.2 1038.61   841.9 1046.47   877.5 1057.55   925.0 1075.04  1001.1 1098.74
#Mann= 3 , 0 , 0
       0     0.1       0   495.1   0.045       0   510.1     0.1       0
Bank Sta=   495.1,   510.1
Exp/Cntr=0.3,0.1

Type RM Length L Ch R = 1 ,1131.3,397.666,400,402.489
XS GIS Cut Line= 3
     1708675.525      321248.243     1708208.668      321428.645
     1707741.811      321609.047
#Sta/Elev= 30
       0 1060.23    57.2 1053.61   139.8 1046.55   170.3 1044.67   258.6 1041.05
   284.8 1038.32   295.9 1036.46   387.7 1013.67   424.4 1001.93   450.3  997.10
   463.0  990.79   488.5  973.83     493  972.39   501.2  969.88     508  970.10
   590.3  981.44   603.0  981.81   628.5  977.51   641.2  977.38   653.9  979.95
   666.7  986.58   679.4  996.50   704.9 1019.44   717.6 1028.30   719.8 1029.06
   730.3 1032.29   806.7 1037.91   819.4 1039.08   828.4 1040.92  1001.0 1095.51
#Mann= 3 , 0 , 0
       0     0.1       0     493   0.045       0     508     0.1       0
Bank Sta=     493,     508
Exp/Cntr=0.3,0.1

Type RM Length L Ch R = 1 ,731.3,480.935,483.777,483.487
XS GIS Cut Line= 3
     1708566.442      320919.665     1708083.437      321050.895
     1707599.557      321178.793
#Sta/Elev= 30
       0 1062.12    51.5 1054.30   100.8 1051.99   137.7 1047.25   190.8 1038.90
   236.1 1033.60   268.1 1026.99   309.9 1019.62   346.8 1015.46   371.4 1011.81
   383.7 1009.01   396.0 1004.81   408.3  998.49   432.9  983.32   445.2  976.97
   452.0  975.29   469.9  973.01     493  967.20   500.3  966.82     508  967.34
   531.3  971.69   607.2  970.63   654.1  974.00   665.5  976.18   764.6 1006.88
   826.0 1022.74   850.0 1027.42   940.7 1037.53   961.1 1043.20  1001.0 1056.91
#Mann= 3 , 0 , 0
       0     0.1       0     493   0.045       0     508     0.1       0
Bank Sta=     493,     508
Exp/Cntr=0.3,0.1

Type RM Length L Ch R = 1 ,247.5,247.105,247.503,250.878
XS GIS Cut Line= 3
     1708476.479      320506.408     1707981.816      320585.220
     1707500.975      320730.976
#Sta/Elev= 30
       0 1022.77     7.4 1021.60    79.5 1004.85    91.5 1003.42   163.7 1002.83
   283.9  996.67   368.0  994.03   392.1  992.06   404.1  989.22   440.2  971.12
   452.2  967.62   476.2  965.45   494.1  962.88   500.3  962.39   509.1  962.65
   549.9  966.60   587.1  968.39   661.5  968.71   686.4  969.83   698.8  972.40
   711.2  978.14   723.6  985.32   736.0  991.54   748.4  995.26   772.4  998.35
   808.0 1001.15   909.7 1006.61   934.5 1007.19   959.3 1006.84  1003.3 1008.00
#Mann= 3 , 0 , 0
       0     0.1       0   494.1   0.045       0   509.1     0.1       0
Bank Sta=   494.1,   509.1
Exp/Cntr=0.3,0.1